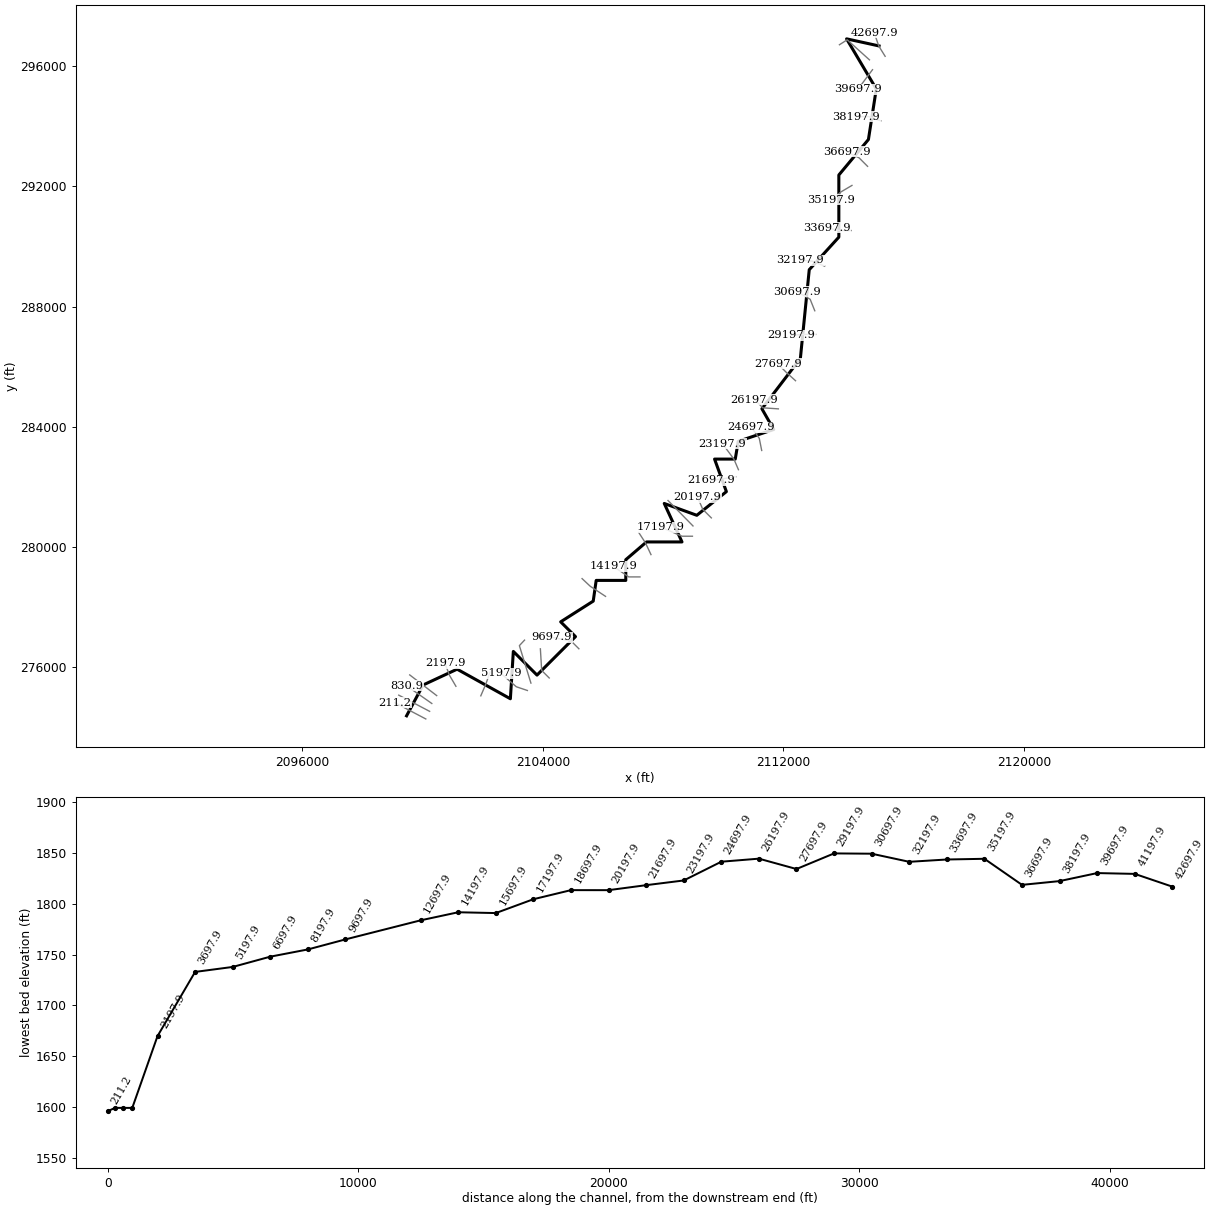
--- MlgnCk1.prj (project) ---

Proj Title=MlgnCk1
Current Plan=p01
Default Exp/Contr=0,0
English Units
Geom File=g01
Flow File=f01
Plan File=p01
BEGIN DESCRIPTION:
END DESCRIPTION:
DSS Export Rating Curves= 0
DSS Export Rating Curve Sorted= 0
DSS Export Volume Flow Curves= 0
DXF OffsetX= 0
DXF OffsetY= 0
DXF ScaleX= 0
DXF ScaleY= 0

--- MlgnCk1.p01 (plan) ---

Plan Title=Floodplain
Program Version=4.00
Geom File=g01
Flow File=f01
K Sum by GR=0
Std Step Tol=0.01
Critical Tol=0.01
Num of Std Step Trials=20
Max Error Tol=0.3
Flow Tol Ratio=0.001
Split Flow NTrial=30
Split Flow Tol=0.02
Split Flow Ratio=0.02
Log Output Level=0
Friction Slope Method=1
Unsteady Friction Slope Method=2
Unsteady Bridges Friction Slope Method=1
Global Log Level=0
CheckData=False
Run HTab=0
Run UNet=0
Run PostProcess=0
UNET Theta=0
UNET Theta Warmup=0
UNET ZTol=0
UNET ZSATol=0
UNET MxIter=0
UNET MaxInSteps=0
UNET DtIC=0
UNET DtMin=0
UNET MaxCRTS=0
UNET WFStab=0
UNET SFStab=0
UNET WFX=0
UNET SFX=0
UNET DSS MLevel=0
UNET DZMax Abort=0
UNET Convert EG Bridges=0
UNET Use Existing IB Tables=0
UNET Froude Limit=0
UNET Froude Power=0
Write IC File=0
Echo Input=False
Echo Output=False
Write Detailed=0

--- MlgnCk1.f01 (steady flow) ---

Flow Title=NFF Regression Equation
Program Version=4.00
Number of Profiles=1
Profile Names=P100yr
River Rch & RM=MlgnCk1,Main      ,42697.9
9622.769
River Rch & RM=MlgnCk1,Main      ,39697.9
9689.436
River Rch & RM=MlgnCk1,Main      ,23197.9
10760.66
River Rch & RM=MlgnCk1,Main      ,23197.9
12201.59
Boundary for River Rch & Prof#=MlgnCk1,Main      ,1
Up Type=0
Dn Type=3
Dn Slope=0.003661

--- MlgnCk1.g01 (geometry) ---

Geom Title=USGS 10m DEM
Program Version=4.00

River Reach=MlgnCk1     ,Main
Reach XY= 30
     2115178.583      296669.668     2114097.792      296906.515
     2115086.073      295238.546     2114824.971      293558.197
     2113840.731      292377.109     2113840.731      290310.205
     2112856.491      289227.541     2112561.219      286274.821
     2111281.707      284601.613     2111675.403      283912.645
     2110494.315      283518.949     2110395.891      282928.405
     2109706.923      282928.405     2110100.619      281845.741
     2109116.379      281058.349     2108033.715      281452.045
     2108624.259      280172.533     2107443.171      280172.533
     2106754.203      279581.989     2106754.203      278893.021
     2105769.963      278893.021     2105671.539      278204.053
     2104588.875      277515.085     2105080.995      277022.965
     2103801.483      275743.453     2103014.091      276530.845
     2102915.667      274956.061     2101144.035      275940.301
     2100011.747      275413.245     2099462.975      274388.656

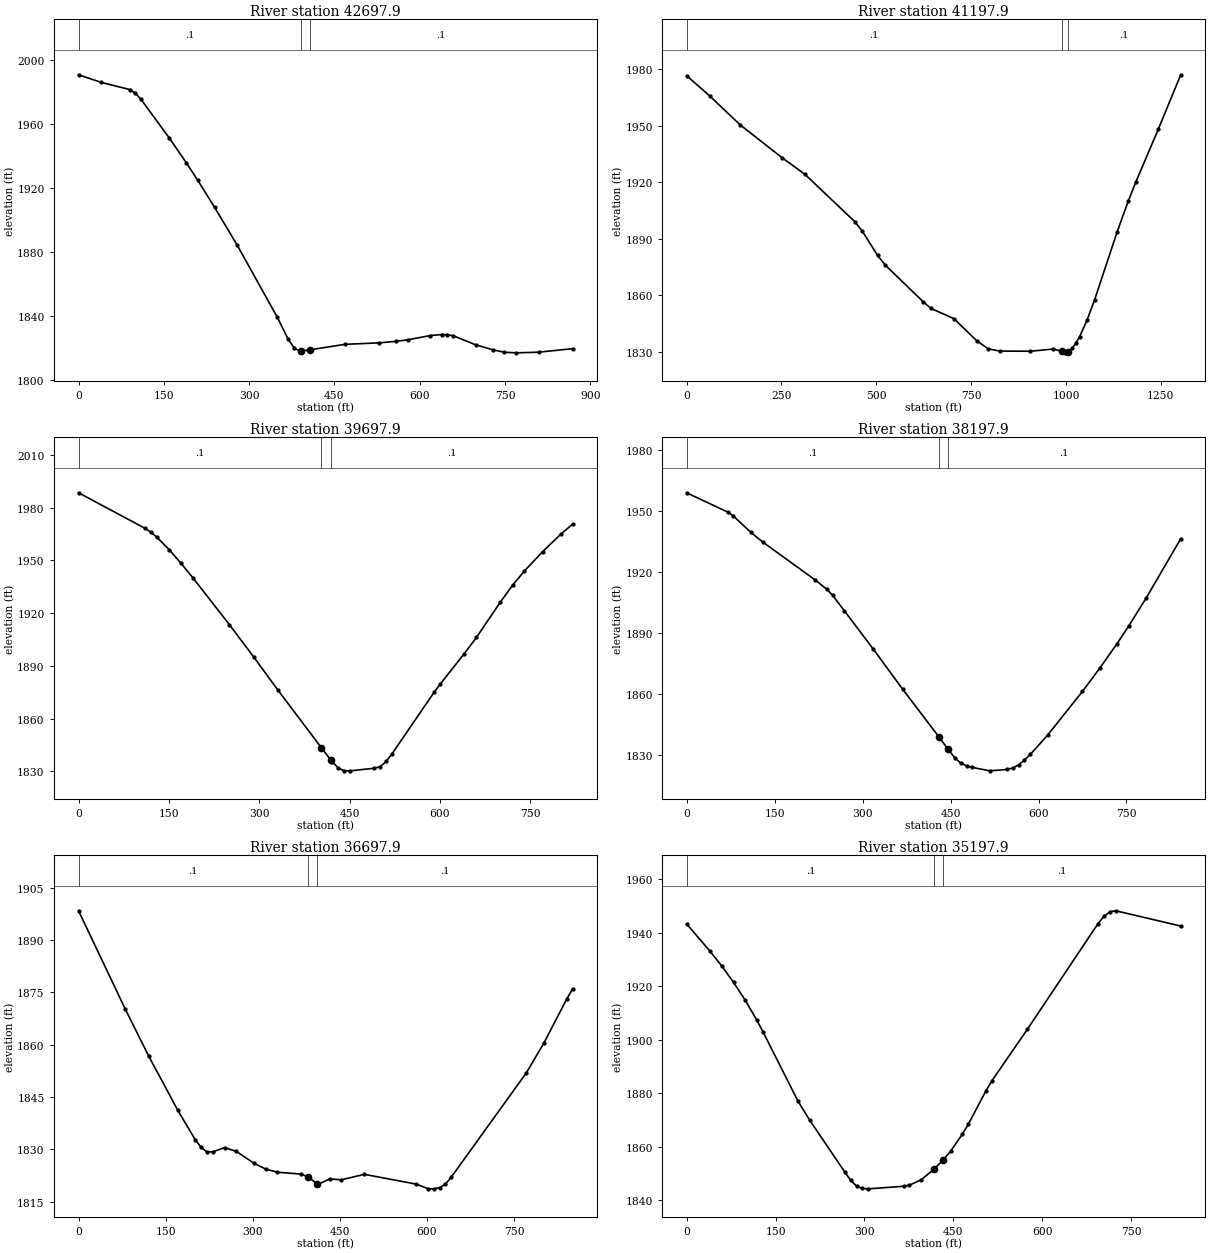
Type RM Length L Ch R = 1 ,42697.9,1539.5,1500,1542.2
XS GIS Cut Line= 3
     2115380.938      296325.319     2115170.407      296663.999
     2115016.804      297108.436
#Sta/Elev= 30
       0 1990.93    39.9 1986.17    89.7 1981.70    99.7 1979.52   109.7 1975.63
   159.5 1951.38   189.4 1935.94   209.4 1925.04   239.3 1907.96   279.2 1884.19
   348.9 1839.60   368.9 1825.36   378.8 1820.14   388.8 1817.94   391.3 1818.01
   406.3 1818.76   468.8 1822.23   528.8 1823.16   558.9 1824.12   578.9 1825.08
   618.9 1827.74   638.9 1828.38   648.9 1828.23   658.9 1827.61   698.9 1821.88
   729.0 1818.78   749.0 1817.30   769.0 1816.91   809.0 1817.31   869.0 1819.52
#Mann= 3 , 0 , 0
       0     0.1       0   391.3   0.045       0   406.3     0.1       0
Bank Sta=   391.3,   406.3
Exp/Cntr=0.3,0.1

Type RM Length L Ch R = 1 ,41197.9,1414.8,1500,1508.2
XS GIS Cut Line= 3
     2114858.954      296207.403     2114118.698      296874.540
     2113860.941      296709.748
#Sta/Elev= 30
       0 1976.68    60.4 1966.01   140.9 1950.60   251.6 1933.11   312.0 1924.25
   442.9 1899.22   463.0 1894.12   503.3 1881.25   523.4 1876.11   624.1 1856.49
   644.2 1853.06   704.6 1847.63   765.0 1835.84   795.2 1831.60   825.4 1830.41
   905.9 1830.32   966.3 1831.48     989 1830.25   996.5 1829.47    1004 1829.86
  1016.3 1831.86  1026.1 1834.69  1036.0 1838.08  1055.7 1846.92  1075.5 1857.71
  1134.7 1893.64  1164.3 1910.14  1184.0 1920.15  1243.2 1948.17  1302.4 1977.17
#Mann= 3 , 0 , 0
       0     0.1       0     989   0.045       0    1004     0.1       0
Bank Sta=     989,    1004
Exp/Cntr=0.3,0.1

Type RM Length L Ch R = 1 ,39697.9,1528.4,1500,1479.3
XS GIS Cut Line= 3
     2114961.075      295879.780     2114715.218      295550.794
     2114470.704      295222.393
#Sta/Elev= 30
       0 1988.38   110.2 1968.20   120.2 1965.89   130.2 1963.04   150.3 1956.10
   170.3 1948.20   190.3 1939.80   250.4 1913.40   290.5 1895.12   330.6 1876.33
   403.2 1843.35   418.2 1836.67   420.7 1835.59   430.7 1832.04   440.7 1830.31
   450.6 1830.28   490.6 1831.74   500.6 1832.67   510.6 1835.62   520.6 1840.09
   590.4 1875.05   600.4 1879.64   640.4 1896.96   660.4 1906.10   700.3 1926.28
   720.3 1935.74   740.2 1943.96   770.2 1954.84   800.2 1964.76   820.1 1970.56
#Mann= 3 , 0 , 0
       0     0.1       0   403.2   0.045       0   418.2     0.1       0
Bank Sta=   403.2,   418.2
Exp/Cntr=0.3,0.1

Type RM Length L Ch R = 1 ,38197.9,1510.9,1500,1489.2
XS GIS Cut Line= 3
     2115239.230      294177.898     2114824.971      294320.183
     2114420.503      294320.183
#Sta/Elev= 30
       0 1958.92    69.7 1949.50    79.6 1947.52   109.5 1939.48   129.4 1934.80
   219.0 1916.15   238.9 1911.58   248.9 1908.51   268.8 1901.05   318.6 1882.02
   368.3 1862.48   430.5 1838.91   445.5 1833.09   457.7 1828.63   467.6 1826.13
   477.5 1824.80   487.3 1824.05   516.9 1822.38   546.5 1823.05   556.4 1823.81
   566.3 1825.37   576.1 1827.65   586.0 1830.41   615.6 1839.94   674.8 1861.34
   704.4 1872.74   734.0 1884.86   753.7 1893.43   783.3 1907.10   842.5 1936.32
#Mann= 3 , 0 , 0
       0     0.1       0   430.5   0.045       0   445.5     0.1       0
Bank Sta=   430.5,   445.5
Exp/Cntr=0.3,0.1

Type RM Length L Ch R = 1 ,36697.9,1468.5,1500,1527.6
XS GIS Cut Line= 3
     2114796.638      292665.126     2114511.905      292949.859
     2114108.719      293145.591
#Sta/Elev= 30
       0 1898.34    80.5 1870.14   120.8 1856.71   171.1 1841.12   201.3 1832.65
   211.4 1830.52   221.5 1829.19   231.5 1829.31   251.7 1830.49   271.8 1829.39
   302.0 1826.02   322.1 1824.34   342.3 1823.43   382.5 1822.91   395.2 1822.14
   410.2 1820.17   412.6 1819.94   432.6 1821.52   452.5 1821.26   492.3 1822.82
   582.0 1820.01   601.9 1818.70   611.8 1818.67   621.8 1819.01   631.8 1820.03
   641.7 1821.98   771.2 1851.91   801.1 1860.34   840.9 1873.10   850.9 1875.93
#Mann= 3 , 0 , 0
       0     0.1       0   395.2   0.045       0   410.2     0.1       0
Bank Sta=   395.2,   410.2
Exp/Cntr=0.3,0.1

Type RM Length L Ch R = 1 ,35197.9,1512.8,1500,1478
XS GIS Cut Line= 3
     2114277.551      292030.791     2113911.064      291814.657
     2113598.778      291551.424
#Sta/Elev= 30
       0 1943.21    39.6 1932.99    59.4 1927.50    79.2 1921.42    99.0 1914.68
   118.7 1907.20   128.6 1903.06   188.0 1877.04   207.8 1869.91   267.2 1850.53
   277.0 1847.48   287.0 1845.32   296.8 1844.46   306.7 1844.33   366.1 1845.29
   376.0 1845.71   395.8 1847.69     418 1851.76     433 1855.13   445.4 1858.33
   465.3 1864.73   475.3 1868.38   505.2 1880.93   515.1 1884.62   574.9 1903.82
   694.4 1943.36   704.4 1946.06   714.4 1947.76   724.3 1948.13   833.9 1942.43
#Mann= 3 , 0 , 0
       0     0.1       0     418   0.045       0     433     0.1       0
Bank Sta=     418,     433
Exp/Cntr=0.3,0.1

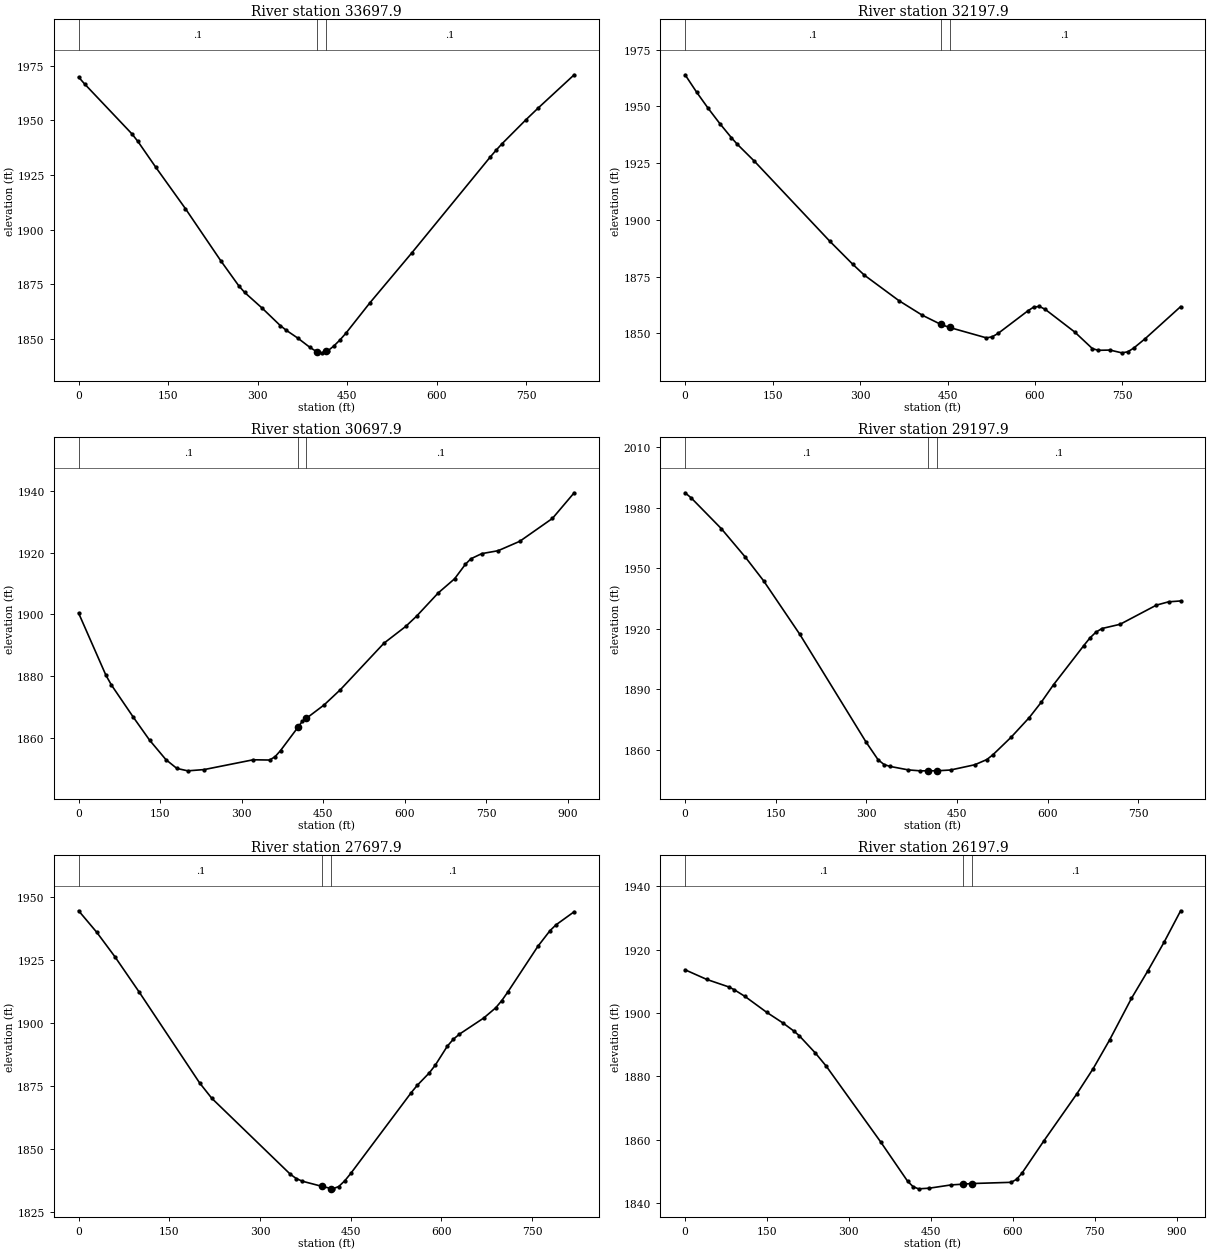
Type RM Length L Ch R = 1 ,33697.9,1509,1500,1503.6
XS GIS Cut Line= 3
     2114247.889      290530.135     2113840.731      290530.135
     2113428.950      290625.906
#Sta/Elev= 30
       0 1969.71     9.9 1966.62    89.4 1943.72    99.3 1940.28   129.1 1928.53
   178.8 1909.59   238.3 1885.65   268.1 1874.33   278.1 1871.24   307.8 1863.97
   337.6 1856.14   347.6 1853.98   367.4 1850.31   387.3 1846.15   397.2 1844.42
   399.7 1844.23   407.2 1843.64   414.7 1844.31   417.2 1844.54   427.3 1846.74
   437.4 1849.46   447.4 1852.54   487.7 1866.48   558.2 1889.42   689.0 1933.07
   699.1 1936.28   709.1 1939.25   749.4 1950.29   769.5 1955.55   829.9 1970.78
#Mann= 3 , 0 , 0
       0     0.1       0   399.7   0.045       0   414.7     0.1       0
Bank Sta=   399.7,   414.7
Exp/Cntr=0.3,0.1

Type RM Length L Ch R = 1 ,32197.9,1519.2,1500,1502.4
XS GIS Cut Line= 3
     2113368.994      289346.336     2112954.915      289512.363
     2112552.347      289540.714
#Sta/Elev= 30
       0 1963.90    19.8 1956.23    39.7 1949.07    59.5 1942.41    79.3 1936.21
    89.2 1933.36   119.0 1925.77   247.8 1890.63   287.5 1880.39   307.3 1875.61
   366.8 1864.33   406.5 1857.97   438.6 1853.89   453.6 1852.53   516.8 1847.95
   526.8 1848.45   536.9 1849.96   587.4 1859.80   597.5 1861.49   607.6 1861.82
   617.6 1860.50   668.1 1850.53   698.4 1843.22   708.4 1842.48   728.6 1842.58
   748.8 1841.36   758.9 1841.80   769.0 1843.41   789.2 1847.67   849.7 1861.73
#Mann= 3 , 0 , 0
       0     0.1       0   438.6   0.045       0   453.6     0.1       0
Bank Sta=   438.6,   453.6
Exp/Cntr=0.3,0.1

Type RM Length L Ch R = 1 ,30697.9,1471.8,1500,1500.8
XS GIS Cut Line= 3
     2113040.571      287861.443     2112887.051      288243.301
     2112456.390      288497.490
#Sta/Elev= 30
       0 1900.39    50.2 1880.29    60.2 1877.16   100.4 1866.76   130.5 1859.28
   160.6 1852.96   180.7 1850.12   200.8 1849.34   230.9 1849.75   321.2 1852.92
   351.3 1852.84   361.4 1853.92   371.4 1855.90   404.1 1863.59   411.6 1865.42
   419.1 1866.36   451.6 1870.68   481.6 1875.63   561.6 1890.65   601.6 1896.08
   621.6 1899.40   661.6 1906.95   691.6 1911.51   711.6 1916.23   721.6 1917.99
   741.6 1919.66   771.6 1920.60   811.6 1923.66   871.6 1931.06   911.6 1939.36
#Mann= 3 , 0 , 0
       0     0.1       0   404.1   0.045       0   419.1     0.1       0
Bank Sta=   404.1,   419.1
Exp/Cntr=0.3,0.1

Type RM Length L Ch R = 1 ,29197.9,1517.5,1500,1479.7
XS GIS Cut Line= 3
     2113068.902      287076.128     2112659.643      287076.128
     2112249.903      287045.729
#Sta/Elev= 30
       0 1987.32    10.0 1984.81    59.9 1969.57    99.8 1955.41   129.8 1943.78
   189.7 1917.29   299.5 1863.87   319.4 1855.12   329.4 1852.73   339.4 1851.81
   369.3 1850.10   389.3 1849.63   401.8 1849.65   416.8 1849.65   439.3 1850.04
   479.4 1852.64   499.4 1855.22   509.5 1857.61   539.5 1866.26   569.6 1876.01
   589.6 1883.66   609.7 1892.26   659.8 1911.65   669.8 1915.37   679.8 1918.27
   689.8 1920.10   719.9 1922.20   780.0 1931.69   800.1 1933.32   820.1 1933.76
#Mann= 3 , 0 , 0
       0     0.1       0   401.8   0.045       0   416.8     0.1       0
Bank Sta=   401.8,   416.8
Exp/Cntr=0.3,0.1

Type RM Length L Ch R = 1 ,27697.9,1481.5,1500,1500
XS GIS Cut Line= 3
     2112400.446      285534.767     2112095.996      285809.598
     2111806.517      286099.077
#Sta/Elev= 30
       0 1944.70    30.0 1936.15    60.0 1926.45   100.0 1912.47   200.1 1876.33
   220.1 1870.26   350.1 1840.06   360.1 1838.33   370.1 1837.29   402.6 1835.24
   417.6 1834.40   420.1 1834.27   430.1 1835.18   440.1 1837.46   450.1 1840.41
   549.9 1872.44   559.9 1875.36   579.9 1880.32   589.9 1883.42   609.8 1890.96
   619.8 1893.71   629.8 1895.71   669.8 1902.09   689.7 1906.15   699.7 1909.00
   709.7 1912.42   759.6 1930.63   779.6 1936.83   789.6 1939.14   819.5 1944.32
#Mann= 3 , 0 , 0
       0     0.1       0   402.6   0.045       0   417.6     0.1       0
Bank Sta=   402.6,   417.6
Exp/Cntr=0.3,0.1

Type RM Length L Ch R = 1 ,26197.9,1533.8,1500,1497.4
XS GIS Cut Line= 3
     2111829.515      284598.886     2111313.721      284633.627
     2111037.570      284909.778
#Sta/Elev= 30
       0 1913.67    39.8 1910.62    79.5 1908.29    89.5 1907.43   109.4 1905.29
   149.1 1900.28   179.0 1896.89   198.8 1894.37   208.8 1892.89   238.6 1887.37
   258.5 1883.22   357.9 1859.35   407.6 1846.84   417.6 1845.14   427.5 1844.46
   447.4 1844.67   487.1 1845.70   509.5 1845.94   524.5 1846.13   597.1 1846.52
   607.1 1847.47   617.1 1849.46   657.2 1859.66   717.2 1874.42   747.3 1882.44
   777.3 1891.47   817.4 1904.63   847.4 1913.33   877.5 1922.49   907.5 1932.32
#Mann= 3 , 0 , 0
       0     0.1       0   509.5   0.045       0   524.5     0.1       0
Bank Sta=   509.5,   524.5
Exp/Cntr=0.3,0.1

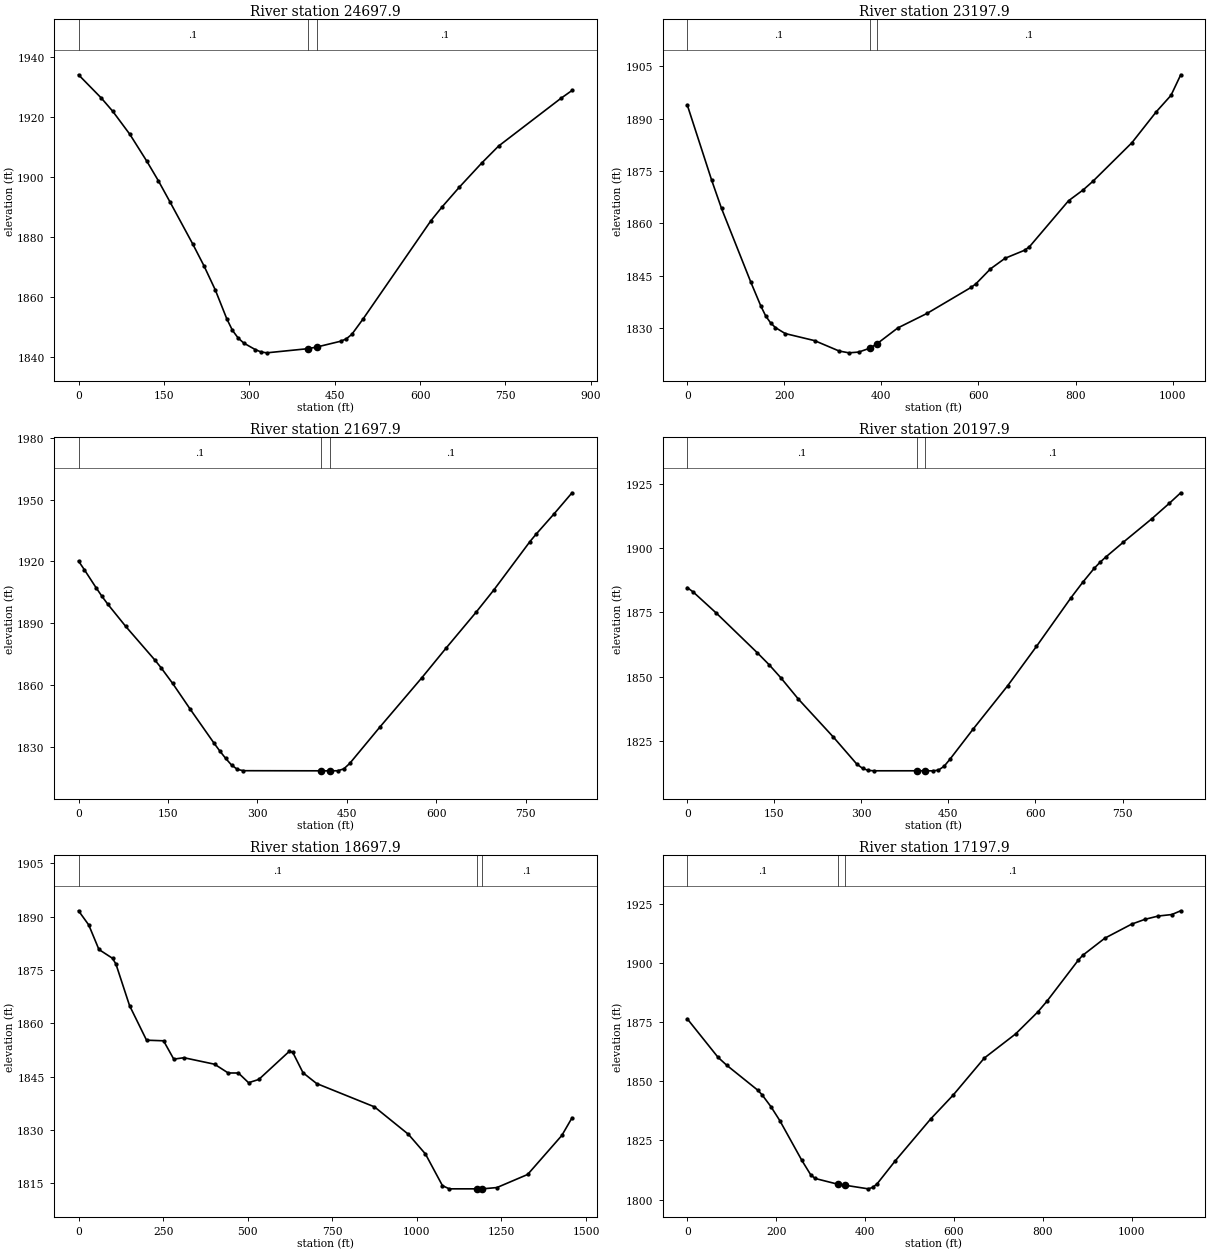
Type RM Length L Ch R = 1 ,24697.9,1494.8,1500,1500.7
XS GIS Cut Line= 3
     2111275.013      283214.572     2111195.025      283617.373
     2110930.503      283989.049
#Sta/Elev= 30
       0 1934.00    40.1 1926.24    60.1 1921.85    90.2 1914.17   120.2 1905.16
   140.2 1898.74   160.3 1891.81   200.3 1877.80   220.4 1870.41   240.4 1862.33
   260.4 1852.80   270.4 1848.94   280.5 1846.37   290.5 1844.68   310.5 1842.54
   320.5 1841.77   330.5 1841.46   403.2 1842.85   418.2 1843.38   460.2 1845.31
   470.2 1846.09   480.1 1847.62   499.9 1852.75   618.9 1885.40   638.8 1890.06
   668.5 1896.50   708.2 1904.62   737.9 1910.28   847.0 1926.11   866.9 1928.78
#Mann= 3 , 0 , 0
       0     0.1       0   403.2   0.045       0   418.2     0.1       0
Bank Sta=   403.2,   418.2
Exp/Cntr=0.3,0.1

Type RM Length L Ch R = 1 ,23197.9,1468.8,1500,1523.7
XS GIS Cut Line= 3
     2110501.349      282575.907     2110350.219      282928.405
     2109972.973      283436.870
#Sta/Elev= 30
       0 1893.91    50.5 1872.29    70.6 1864.30   131.2 1843.14   151.4 1836.46
   161.5 1833.58   171.6 1831.59   181.7 1830.22   201.9 1828.51   262.4 1826.49
   312.9 1823.52   333.1 1823.00   353.2 1823.22     376 1824.32     391 1825.60
   433.8 1830.12   494.1 1834.28   584.5 1841.69   594.6 1842.72   624.7 1847.01
   654.9 1850.05   695.1 1852.34   705.1 1853.35   785.5 1866.48   815.7 1869.59
   835.8 1872.06   916.2 1883.10   966.4 1891.95   996.6 1896.62  1016.7 1902.51
#Mann= 3 , 0 , 0
       0     0.1       0     376   0.045       0     391     0.1       0
Bank Sta=     376,     391
Exp/Cntr=0.3,0.1

Type RM Length L Ch R = 1 ,21697.9,1522.2,1500,1469.3
XS GIS Cut Line= 3
     2110411.917      282339.842     2110002.195      282275.545
     2109592.918      282218.474
#Sta/Elev= 30
       0 1920.18     9.9 1915.94    29.6 1907.18    39.5 1903.00    49.4 1899.14
    79.0 1888.54   128.4 1872.04   138.2 1868.52   158.0 1860.77   187.6 1848.20
   227.1 1831.90   237.0 1828.01   246.9 1824.40   256.7 1821.19   266.6 1819.07
   276.5 1818.44   407.2 1818.38   422.2 1818.37   434.9 1818.41   445.0 1819.31
   455.0 1821.96   505.4 1839.55   576.0 1863.55   616.3 1877.81   666.7 1895.24
   697.0 1906.23   757.4 1929.65   767.5 1933.17   797.7 1943.05   828.0 1953.33
#Mann= 3 , 0 , 0
       0     0.1       0   407.2   0.045       0   422.2     0.1       0
Bank Sta=   407.2,   422.2
Exp/Cntr=0.3,0.1

Type RM Length L Ch R = 1 ,20197.9,1496.5,1500,1490.3
XS GIS Cut Line= 3
     2109599.872      280972.194     2109315.048      281257.018
     2109138.111      281668.003
#Sta/Elev= 30
       0 1884.65    10.1 1882.97    50.4 1874.67   120.8 1859.31   141.0 1854.70
   161.1 1849.65   191.3 1841.38   251.8 1826.57   292.0 1816.12   302.1 1814.42
   312.2 1813.61   322.2 1813.48   395.3 1813.48   410.3 1813.48   422.7 1813.46
   432.6 1813.71   442.6 1815.24   452.5 1817.92   492.3 1829.59   552.0 1846.49
   601.7 1861.79   661.3 1880.73   681.2 1886.63   701.1 1892.10   711.0 1894.42
   721.0 1896.48   750.8 1902.17   800.5 1911.39   830.4 1917.34   850.3 1921.47
#Mann= 3 , 0 , 0
       0     0.1       0   395.3   0.045       0   410.3     0.1       0
Bank Sta=   395.3,   410.3
Exp/Cntr=0.3,0.1

Type RM Length L Ch R = 1 ,18697.9,1484.8,1500,1527.6
XS GIS Cut Line= 2
     2108989.852      280704.045     2108158.838      281550.469
#Sta/Elev= 30
       0 1891.69    30.2 1887.70    60.3 1880.80   100.5 1878.32   110.6 1876.69
   150.8 1865.02   201.0 1855.29   251.3 1855.12   281.5 1849.96   311.6 1850.36
   402.1 1848.53   442.3 1846.07   472.5 1846.06   502.6 1843.33   532.8 1844.25
   623.2 1852.18   633.3 1851.85   663.5 1846.13   703.7 1843.10   874.6 1836.54
   975.1 1828.81  1025.3 1823.29  1075.6 1814.38  1095.7 1813.48  1178.7 1813.48
  1193.7 1813.48  1236.6 1813.84  1327.4 1817.52  1428.4 1828.49  1458.6 1833.46
#Mann= 3 , 0 , 0
       0     0.1       0  1178.7   0.045       0  1193.7     0.1       0
Bank Sta=  1178.7,  1193.7
Exp/Cntr=0.3,0.1

Type RM Length L Ch R = 1 ,17197.9,1526.7,1500,1486.2
XS GIS Cut Line= 3
     2108971.301      280362.548     2108624.259      280362.548
     2107922.729      280663.673
#Sta/Elev= 30
       0 1876.33    69.4 1860.05    89.2 1856.67   158.6 1846.21   168.6 1844.20
   188.4 1839.22   208.2 1833.38   257.8 1816.59   277.6 1810.54   287.6 1808.93
   339.5 1806.46   354.5 1806.08   407.3 1804.54   417.4 1805.15   427.4 1806.69
   467.6 1816.25   547.9 1834.07   598.2 1844.08   668.5 1859.76   738.8 1869.93
   789.0 1879.25   809.1 1883.68   879.4 1900.95   889.5 1903.07   939.7 1910.37
  1000.0 1916.30  1030.1 1918.34  1060.2 1919.73  1090.4 1920.35  1110.5 1921.94
#Mann= 3 , 0 , 0
       0     0.1       0   339.5   0.045       0   354.5     0.1       0
Bank Sta=   339.5,   354.5
Exp/Cntr=0.3,0.1

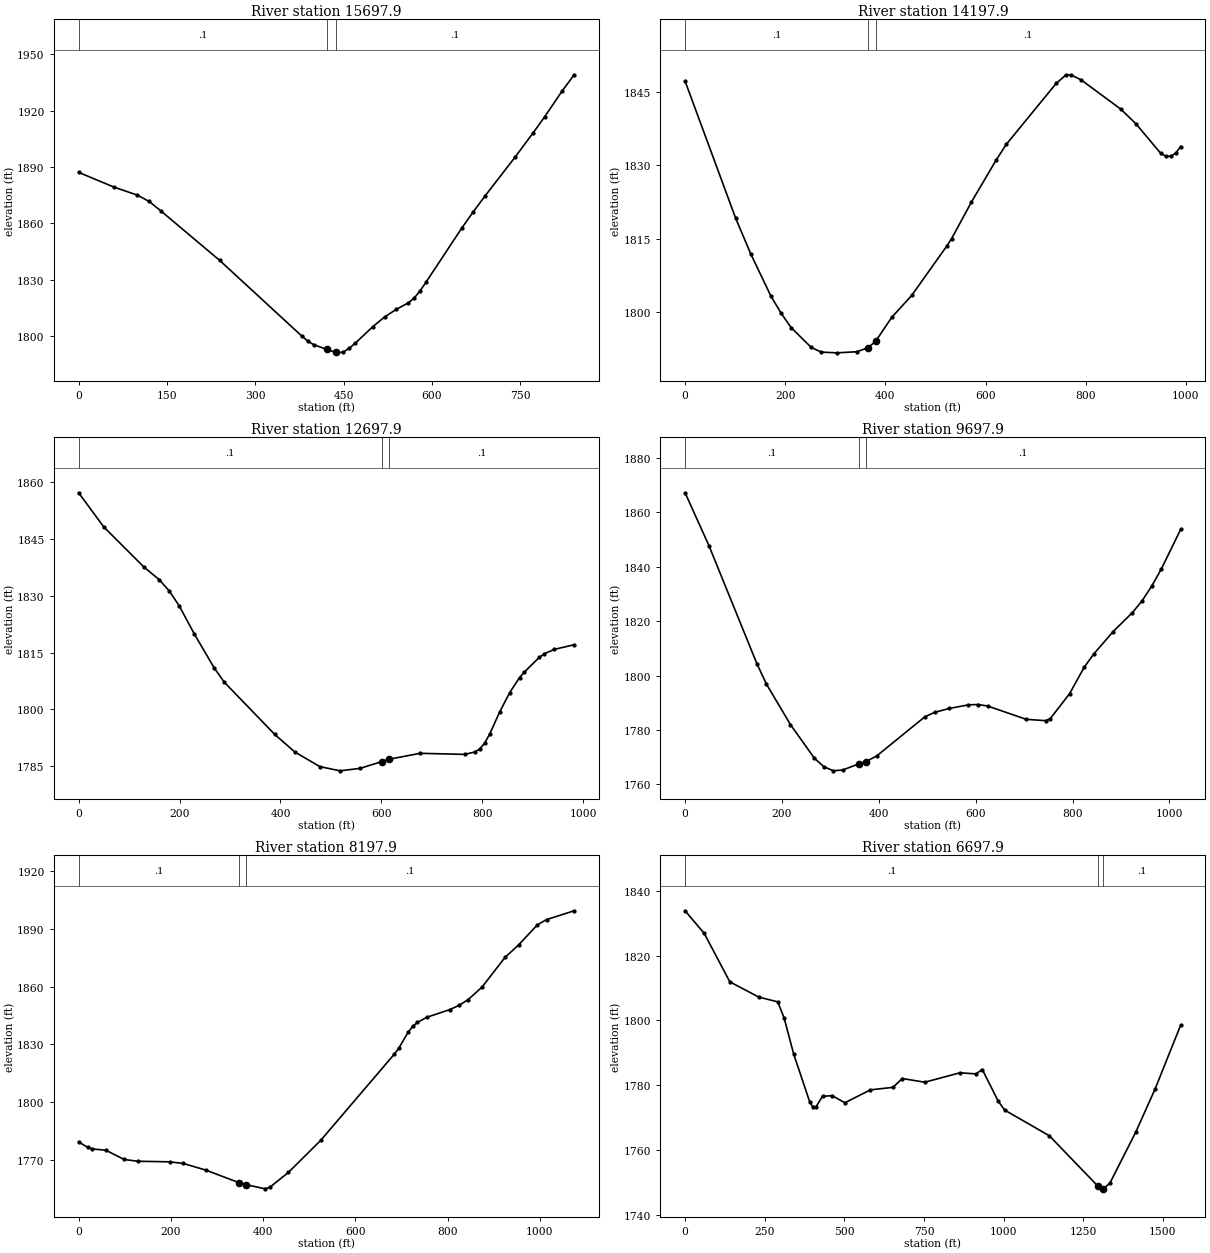
Type RM Length L Ch R = 1 ,15697.9,1473.3,1500,1508
XS GIS Cut Line= 3
     2107592.616      279750.743     2107409.682      280139.045
     2107185.708      280485.685
#Sta/Elev= 30
       0 1887.13    59.9 1879.26    99.8 1874.99   119.8 1871.60   139.8 1866.54
   239.6 1840.19   379.3 1799.82   389.3 1797.21   399.3 1795.24   421.7 1792.76
   436.7 1791.15   439.3 1790.91   449.4 1791.32   459.4 1793.26   469.5 1795.91
   499.7 1804.84   519.8 1810.02   540.0 1814.16   560.1 1817.54   570.2 1820.14
   580.2 1824.00   590.3 1828.62   650.7 1857.30   670.8 1866.25   691.0 1874.75
   741.3 1895.15   771.5 1907.88   791.6 1916.66   821.8 1930.62   841.9 1939.13
#Mann= 3 , 0 , 0
       0     0.1       0   421.7   0.045       0   436.7     0.1       0
Bank Sta=   421.7,   436.7
Exp/Cntr=0.3,0.1

Type RM Length L Ch R = 1 ,14197.9,1514.7,1500,1497.5
XS GIS Cut Line= 3
     2107225.542      279008.977     2106852.627      279008.977
     2106344.066      279358.010
#Sta/Elev= 30
       0 1847.18   100.8 1819.25   131.0 1811.94   171.3 1803.31   191.5 1799.85
   211.6 1796.88   252.0 1792.81   272.1 1791.86   302.4 1791.71   342.7 1791.93
   365.4 1792.75   380.4 1794.05   412.7 1798.96   452.5 1803.42   522.1 1813.44
   532.1 1815.00   571.9 1822.51   621.6 1831.14   641.5 1834.28   741.0 1846.71
   760.9 1848.49   770.9 1848.45   790.8 1847.46   870.3 1841.46   900.2 1838.51
   949.9 1832.45   959.9 1831.85   969.8 1831.86   979.8 1832.48   989.7 1833.84
#Mann= 3 , 0 , 0
       0     0.1       0   365.4   0.045       0   380.4     0.1       0
Bank Sta=   365.4,   380.4
Exp/Cntr=0.3,0.1

Type RM Length L Ch R = 1 ,12697.9,3005.8,3000,3006.9
XS GIS Cut Line= 3
     2106080.923      278361.979     2105573.742      278696.800
     2105300.565      278952.658
#Sta/Elev= 30
       0 1857.24    49.8 1848.22   129.5 1837.61   159.4 1834.32   179.3 1831.35
   199.3 1827.36   229.1 1819.97   269.0 1810.87   288.9 1807.15   388.6 1793.39
   428.4 1788.74   478.2 1784.87   518.1 1783.76   557.9 1784.42   600.2 1786.18
   615.2 1786.82   676.7 1788.39   765.3 1788.11   785.0 1788.75   794.9 1789.53
   804.7 1791.11   814.6 1793.48   834.3 1799.30   854.0 1804.36   873.7 1808.41
   883.5 1809.89   913.1 1813.78   922.9 1814.70   942.6 1815.86   982.0 1817.08
#Mann= 3 , 0 , 0
       0     0.1       0   600.2   0.045       0   615.2     0.1       0
Bank Sta=   600.2,   615.2
Exp/Cntr=0.3,0.1

Type RM Length L Ch R = 1 ,9697.9,1500,1500,1464.7
XS GIS Cut Line= 3
     2105194.402      276619.121     2104935.776      276877.746
     2104289.799      276999.792
#Sta/Elev= 30
       0 1867.22    49.4 1847.71   148.3 1804.37   168.0 1796.87   217.5 1782.02
   266.9 1769.65   286.7 1766.49   306.4 1765.00   326.2 1765.36   358.3 1767.53
   373.3 1768.38   395.6 1770.47   495.2 1784.89   515.2 1786.48   545.0 1787.92
   584.9 1789.25   604.8 1789.38   624.7 1788.83   704.4 1783.94   744.3 1783.44
   754.2 1784.23   794.1 1793.42   823.9 1803.05   843.9 1807.97   883.7 1816.17
   923.6 1823.17   943.5 1827.46   963.4 1832.90   983.3 1839.19  1023.2 1853.74
#Mann= 3 , 0 , 0
       0     0.1       0   358.3   0.045       0   373.3     0.1       0
Bank Sta=   358.3,   373.3
Exp/Cntr=0.3,0.1

Type RM Length L Ch R = 1 ,8197.9,1494.7,1500,1483.4
XS GIS Cut Line= 3
     2104207.526      275647.750     2103956.653      275898.623
     2103913.662      276616.870
#Sta/Elev= 30
       0 1779.50    19.7 1776.58    29.6 1775.81    59.1 1775.16    98.6 1770.35
   128.1 1769.43   197.1 1769.13   226.7 1768.29   276.0 1764.82   347.3 1758.35
   362.3 1757.32   404.8 1755.12   414.8 1755.98   454.7 1763.62   524.7 1780.23
   684.6 1825.06   694.6 1828.27   714.6 1836.47   724.6 1839.48   734.5 1841.44
   754.5 1844.09   804.5 1848.07   824.5 1850.26   844.5 1853.29   874.4 1859.73
   924.4 1875.17   954.4 1881.78   994.4 1892.04  1014.4 1894.78  1074.3 1899.35
#Mann= 3 , 0 , 0
       0     0.1       0   347.3   0.045       0   362.3     0.1       0
Bank Sta=   347.3,   362.3
Exp/Cntr=0.3,0.1

Type RM Length L Ch R = 1 ,6697.9,1486.5,1500,1537.5
XS GIS Cut Line= 3
     2103599.316      275477.202     2103215.146      276723.486
     2103387.086      276907.063
#Sta/Elev= 30
       0 1833.85    60.2 1826.84   140.4 1811.92   230.7 1807.23   290.9 1805.72
   311.0 1800.72   341.1 1789.54   391.2 1774.87   401.3 1773.21   411.3 1773.38
   431.4 1776.57   461.5 1776.77   501.6 1774.58   581.8 1778.56   652.1 1779.33
   682.2 1782.06   752.4 1780.91   862.8 1783.83   912.9 1783.49   933.0 1784.84
   983.1 1775.06  1003.2 1772.32  1143.6 1764.38  1296.7 1748.75  1311.7 1748.02
  1314.2 1748.00  1334.3 1749.90  1414.8 1765.51  1475.2 1778.76  1555.7 1798.52
#Mann= 3 , 0 , 0
       0     0.1       0  1296.7   0.045       0  1311.7     0.1       0
Bank Sta=  1296.7,  1311.7
Exp/Cntr=0.3,0.1

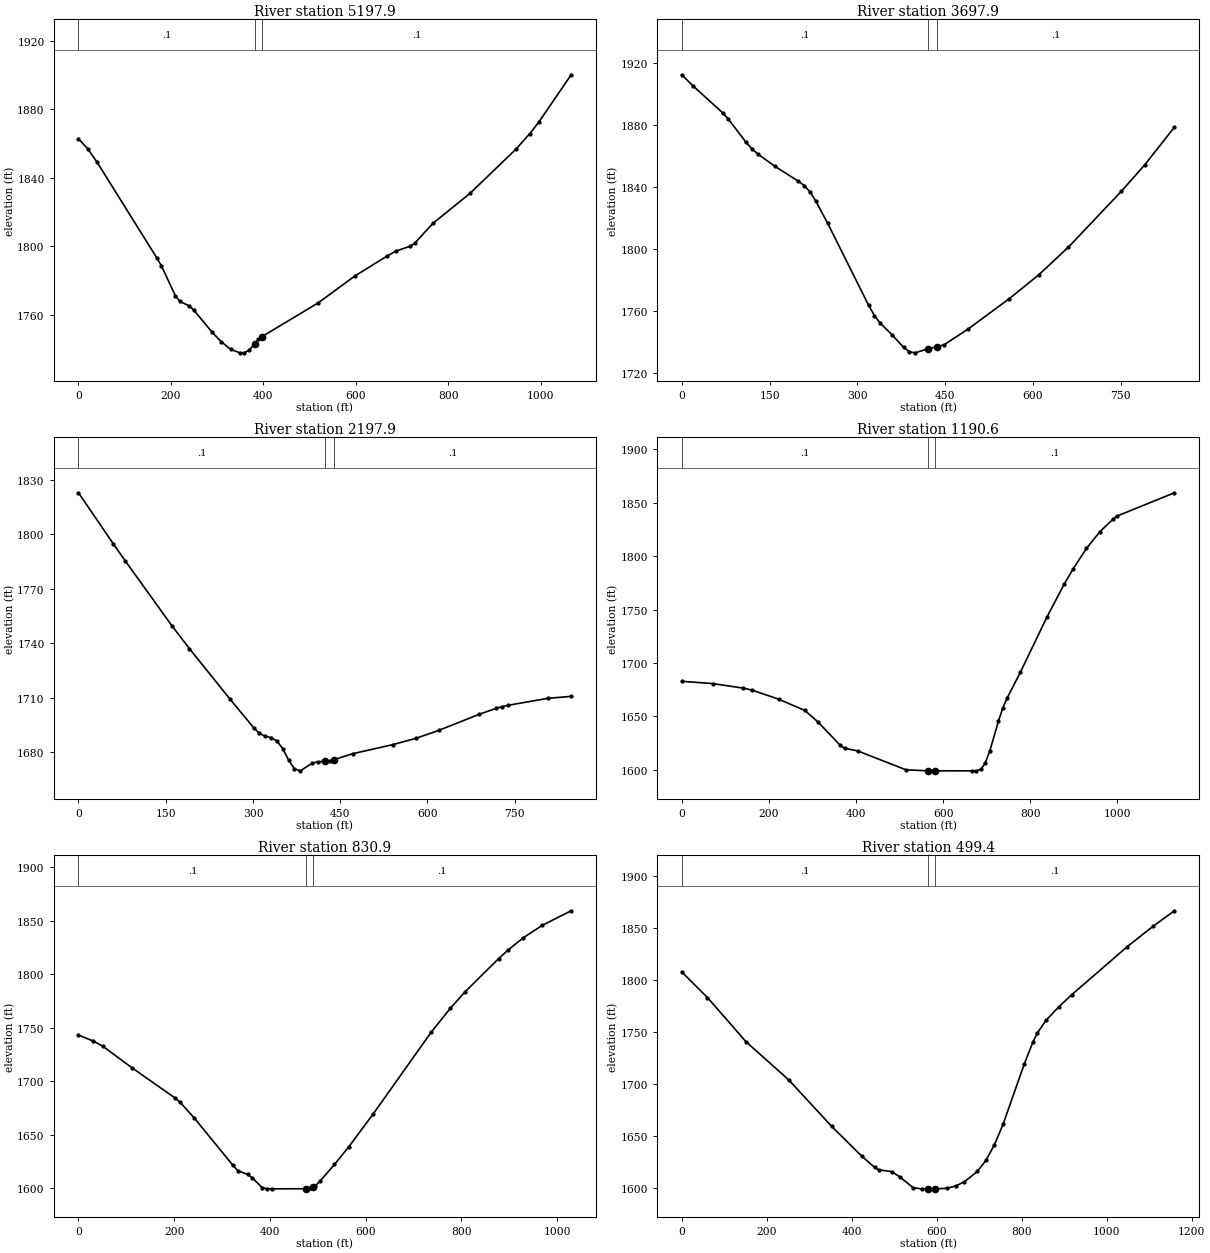
Type RM Length L Ch R = 1 ,5197.9,1539.3,1500,1474.4
XS GIS Cut Line= 3
     2103481.095      275231.631     2103112.515      275355.949
     2102601.516      275799.850
#Sta/Elev= 30
       0 1862.79    20.0 1856.88    39.9 1849.23   169.6 1793.21   179.5 1788.58
   209.4 1771.32   219.4 1767.86   239.4 1765.32   249.4 1762.84   289.2 1749.91
   309.2 1744.30   329.1 1739.96   349.1 1737.89   359.1 1737.97   369.0 1739.40
   381.5 1743.19   389.0 1745.70   396.5 1747.27   518.4 1766.99   598.0 1782.72
   667.7 1794.36   687.6 1797.33   717.5 1800.04   727.4 1801.83   767.2 1813.49
   846.9 1830.85   946.4 1856.66   976.3 1865.70   996.2 1872.58  1065.9 1900.08
#Mann= 3 , 0 , 0
       0     0.1       0   381.5   0.045       0   396.5     0.1       0
Bank Sta=   381.5,   396.5
Exp/Cntr=0.3,0.1

Type RM Length L Ch R = 1 ,3697.9,1477.2,1500,1516.2
XS GIS Cut Line= 3
     2101932.107      275053.905     2102100.935      275448.181
     2102237.420      275838.027
#Sta/Elev= 30
       0 1912.62    20.0 1905.19    69.8 1888.07    79.8 1883.91   109.7 1869.05
   119.7 1864.87   129.7 1861.50   159.6 1853.38   199.5 1843.82   209.5 1841.00
   219.4 1836.89   229.4 1830.81   249.4 1816.67   319.2 1763.81   329.2 1757.11
   339.1 1752.18   359.1 1744.78   379.0 1736.59   389.0 1733.72   399.0 1732.99
   421.4 1735.75   436.4 1736.91   449.0 1738.34   489.4 1748.38   559.9 1768.02
   610.2 1783.41   660.6 1801.20   751.3 1837.34   791.6 1854.59   842.0 1878.78
#Mann= 3 , 0 , 0
       0     0.1       0   421.4   0.045       0   436.4     0.1       0
Bank Sta=   421.4,   436.4
Exp/Cntr=0.3,0.1

Type RM Length L Ch R = 1 ,2197.9,996.8,1007.3,1022
XS GIS Cut Line= 3
     2101104.586      275371.050     2100886.315      275743.453
     2100742.737      276133.256
#Sta/Elev= 30
       0 1822.89    60.2 1794.64    80.3 1785.47   160.6 1749.68   190.7 1737.13
   261.0 1709.12   301.2 1693.58   311.2 1690.41   321.2 1688.80   331.3 1688.12
   341.3 1686.19   351.4 1681.94   361.4 1675.69   371.4 1670.94   381.5 1669.82
   401.5 1673.96   411.6 1674.79   424.2 1675.09   431.7 1675.25   439.2 1675.96
   471.2 1679.23   540.4 1684.24   580.0 1687.69   619.6 1692.11   688.8 1700.91
   718.5 1704.26   728.4 1705.14   738.3 1705.88   807.5 1709.76   847.1 1710.80
#Mann= 3 , 0 , 0
       0     0.1       0   424.2   0.045       0   439.2     0.1       0
Bank Sta=   424.2,   439.2
Exp/Cntr=0.3,0.1

Type RM Length L Ch R = 1 ,1190.6,358.8,359.7,361
XS GIS Cut Line= 2
     2100464.767      275061.325     2099567.682      275749.585
#Sta/Elev= 30
       0 1682.89    70.7 1680.76   141.3 1676.50   161.5 1674.60   222.1 1666.19
   282.7 1655.60   313.0 1644.71   363.4 1623.11   373.5 1620.33   403.8 1617.77
   514.9 1600.08   565.9 1599.18   580.9 1599.18   666.3 1599.15   676.4 1599.21
   686.5 1600.51   696.6 1606.60   706.7 1617.44   726.9 1645.68   737.0 1658.19
   747.1 1667.47   777.4 1691.57   837.9 1742.81   878.3 1774.22   898.5 1788.19
   928.8 1807.13   959.1 1822.52   989.4 1834.40   999.4 1837.46  1130.7 1859.18
#Mann= 3 , 0 , 0
       0     0.1       0   565.9   0.045       0   580.9     0.1       0
Bank Sta=   565.9,   580.9
Exp/Cntr=0.3,0.1

Type RM Length L Ch R = 1 ,830.9,328.6,331.5,334.5
XS GIS Cut Line= 2
     2100302.519      274799.200     2099459.730      275390.085
#Sta/Elev= 30
       0 1743.05    30.3 1737.56    50.5 1732.75   111.0 1712.67   201.8 1684.18
   211.9 1680.38   242.2 1665.30   322.9 1621.05   333.0 1616.14   353.2 1612.64
   363.3 1609.43   383.5 1600.38   393.6 1599.23   403.6 1599.17   475.8 1599.27
   484.4 1599.73   490.8 1601.13   494.5 1601.92   504.6 1606.40   534.8 1621.96
   565.1 1638.71   615.6 1669.17   736.6 1745.56   777.0 1768.20   807.3 1783.36
   877.9 1814.65   898.1 1822.82   928.4 1833.80   968.7 1845.70  1029.3 1859.38
#Mann= 3 , 0 , 0
       0     0.1       0   475.8   0.045       0   490.8     0.1       0
Bank Sta=   475.8,   490.8
Exp/Cntr=0.3,0.1

Type RM Length L Ch R = 1 ,499.4,288.2,288.1,288.1
XS GIS Cut Line= 2
     2100229.487      274537.902     2099203.058      275076.729
#Sta/Elev= 30
       0 1807.78    60.5 1783.14   151.2 1740.65   252.0 1703.85   352.8 1659.20
   423.4 1630.69   453.6 1619.86   463.7 1617.46   494.0 1615.73   514.1 1610.38
   544.4 1600.26   564.5 1599.18   580.1 1599.18   595.1 1599.19   625.0 1599.72
   645.2 1602.11   665.3 1606.00   695.6 1615.99   715.7 1626.48   735.9 1641.70
   756.0 1661.22   806.4 1719.69   826.6 1740.55   836.7 1748.97   856.8 1761.08
   887.1 1774.20   917.3 1785.75  1048.4 1832.11  1108.9 1851.66  1159.3 1866.60
#Mann= 3 , 0 , 0
       0     0.1       0   580.1   0.045       0   595.1     0.1       0
Bank Sta=   580.1,   595.1
Exp/Cntr=0.3,0.1

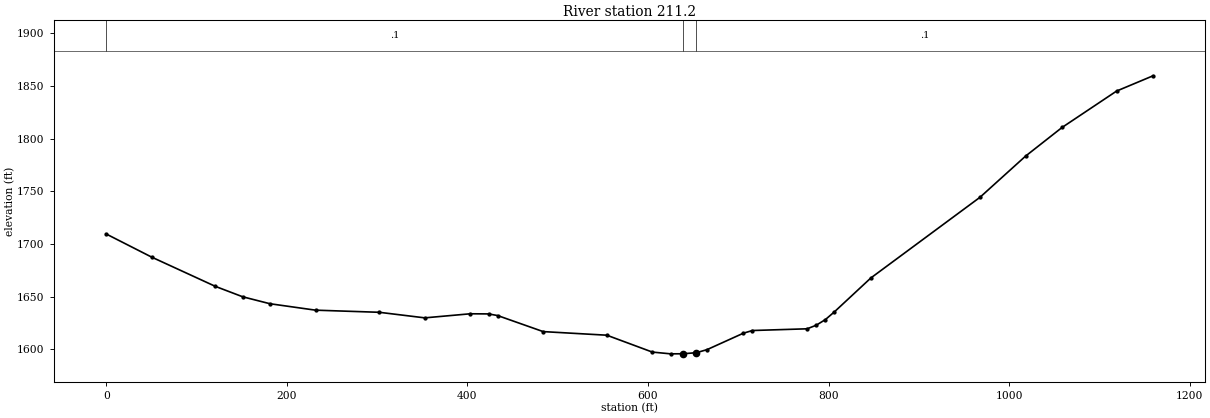
Type RM Length L Ch R = 1 ,211.2,202.6,211.2,219.8
XS GIS Cut Line= 2
     2100102.632      274284.734     2099076.203      274823.561
#Sta/Elev= 30
       0 1709.61    50.4 1687.64   121.0 1659.86   151.2 1650.00   181.4 1643.41
   231.8 1637.32   302.4 1635.30   352.8 1630.02   403.2 1633.89   423.4 1633.76
   433.5 1632.20   483.9 1616.98   554.4 1613.56   604.8 1597.54   625.0 1595.88
   638.6 1595.94   653.6 1596.98   665.3 1599.84   705.6 1615.46   715.7 1618.01
   776.2 1619.64   786.3 1623.04   796.4 1628.36   806.4 1635.72   846.8 1667.89
   967.7 1744.47  1018.1 1783.49  1058.5 1810.67  1118.9 1845.22  1159.3 1859.72
#Mann= 3 , 0 , 0
       0     0.1       0   638.6   0.045       0   653.6     0.1       0
Bank Sta=   638.6,   653.6
Exp/Cntr=0.3,0.1